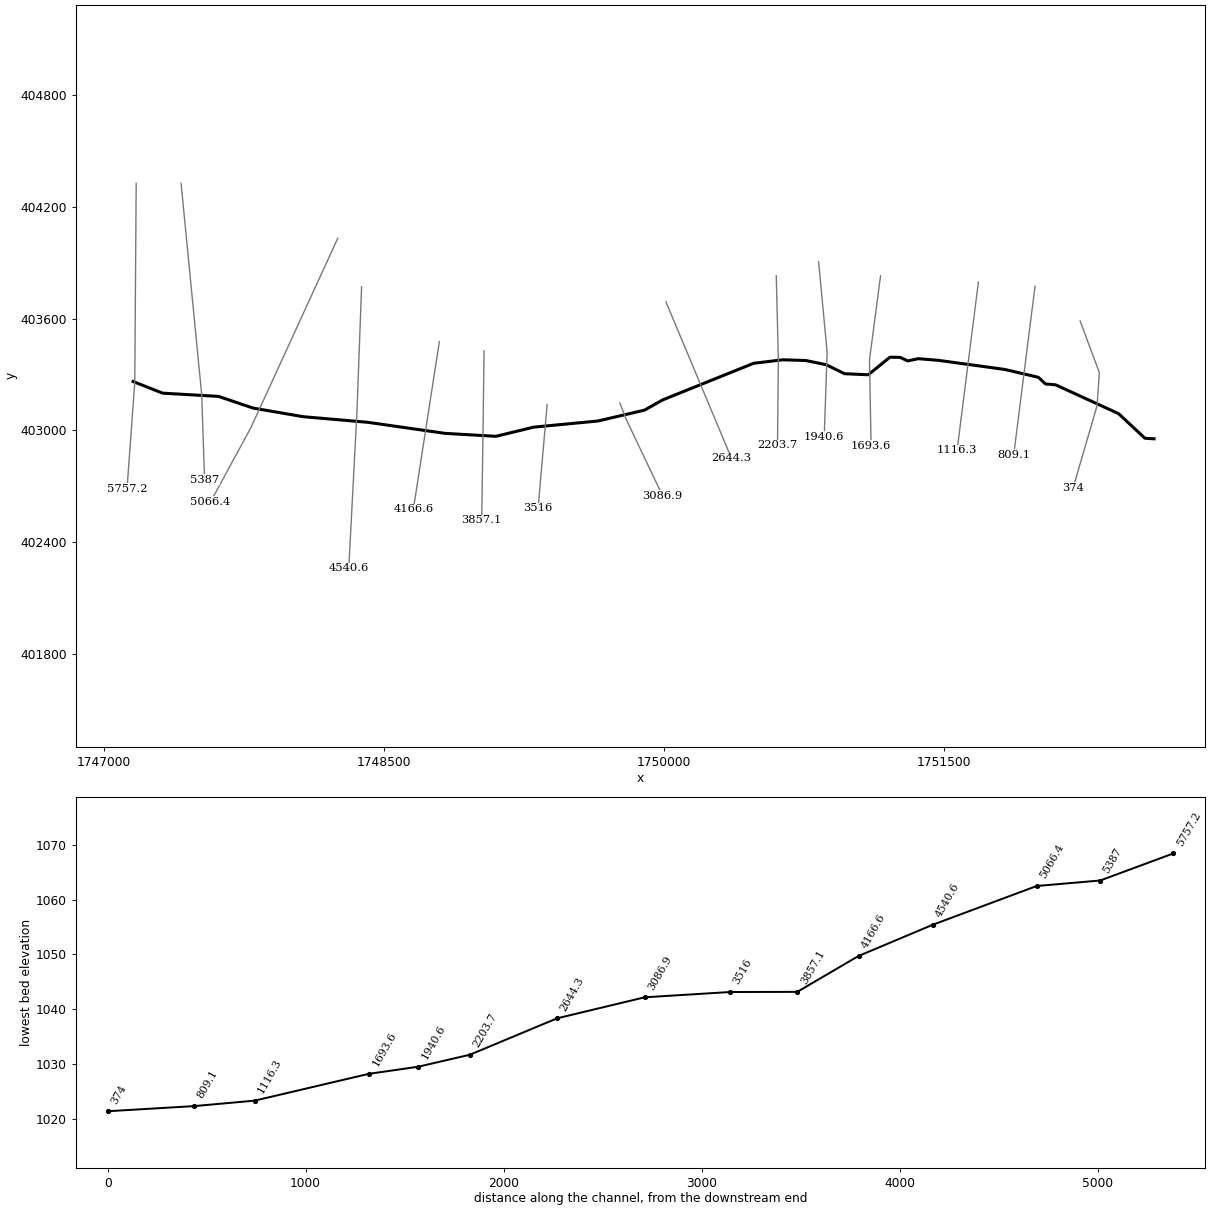
--- SgrRn.prj (project) ---

Proj Title=SgrRn
Current Plan=p01
Geom File=g01
Flow File=f01
Plan File=p01
DSS Export Rating Curves=0
DSS Export Rating Curve Sorted=0
DSS Export Volume Flow Curves=0
DXF OffsetX=0
DXF OffsetY=0
DXF ScaleX=0
DXF ScaleY=0

--- SgrRn.p01 (plan) ---

Plan Title=Floodplain
Program Version=4.00
Geom File=g01
Flow File=f01
K Sum by GR=0
Std Step Tol=0.01
Critical Tol=0.01
Num of Std Step Trials=20
Max Error Tol=0.3
Flow Tol Ratio=0.001
Split Flow NTrial=30
Split Flow Tol=0.02
Split Flow Ratio=0.02
Log Output Level=0
Friction Slope Method=1
Unsteady Friction Slope Method=2
Unsteady Bridges Friction Slope Method=1
Global Log Level=0
CheckData=False
Run HTab=0
Run UNet=0
Run PostProcess=0
UNET Theta=0
UNET Theta Warmup=0
UNET ZTol=0
UNET ZSATol=0
UNET MxIter=0
UNET MaxInSteps=0
UNET DtIC=0
UNET DtMin=0
UNET MaxCRTS=0
UNET WFStab=0
UNET SFStab=0
UNET WFX=0
UNET SFX=0
UNET DSS MLevel=0
UNET DZMax Abort=0
UNET Convert EG Bridges=0
UNET Use Existing IB Tables=0
UNET Froude Limit=0
UNET Froude Power=0
Write IC File=0
Echo Input=False
Echo Output=False
Write Detailed=0

--- SgrRn.f01 (steady flow) ---

Flow Title=NFF Regression Equation
Program Version=4.00
Number of Profiles=1
Profile Names=P100yr
River Rch & RM=SgrRn,Main      ,5757.2
734.7888
River Rch & RM=SgrRn,Main      ,5387
739.0180
River Rch & RM=SgrRn,Main      ,4540.6
820.4076
River Rch & RM=SgrRn,Main      ,2644.3
870.4608
River Rch & RM=SgrRn,Main      ,374
965.1096
Boundary for River Rch & Prof#=SgrRn,Main      ,1
Up Type=0
Dn Type=3
Dn Slope=0.005634

--- SgrRn.g01 (geometry) ---

Geom Title=USGS 3m DEM
Program Version=4.00

River Reach=SgrRn     ,Main
Reach XY= 30
     1747155.946      403262.040     1747314.132      403199.382
     1747614.070      403181.920     1747798.963      403119.262
     1748067.756      403072.925     1748412.290      403043.006
     1748829.295      402983.276     1749100.861      402967.581
     1749303.558      403016.886     1749646.866      403049.756
     1749897.042      403108.191     1749993.826      403162.974
     1750481.417      403359.686     1750638.540      403378.606
     1750760.843      403374.623     1750870.611      403352.063
     1750968.586      403303.836     1751095.787      403298.102
     1751211.991      403392.423     1751266.964      403391.463
     1751307.752      403372.427     1751363.357      403384.529
     1751471.731      403375.662     1751828.828      403326.500
     1752007.817      403284.301     1752045.631      403248.744
     1752099.723      403244.130     1752437.124      403089.567
     1752578.785      402957.074     1752627.602      402954.215

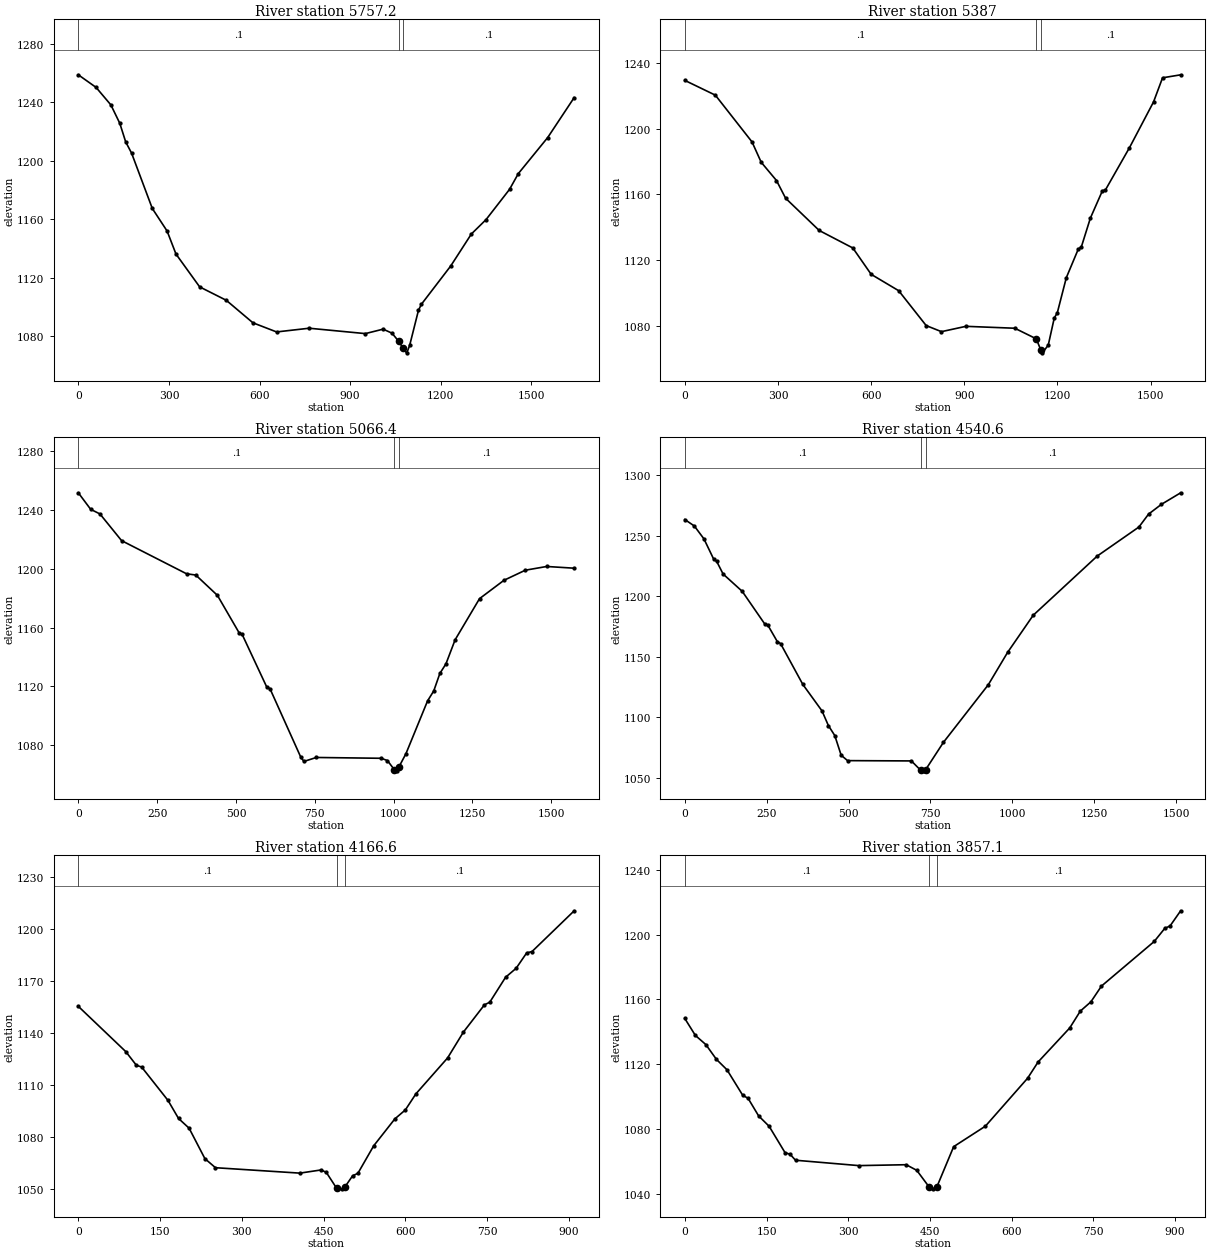
Type RM Length L Ch R = 1 ,5757.2,368.157,370.166,372.529
XS GIS Cut Line= 3
     1747172.590      404325.944     1747165.130      403258.084
     1747123.484      402685.809
#Sta/Elev= 30
       0 1258.74    58.8 1250.13   107.8 1238.15   137.2 1225.62   156.8 1212.88
   176.3 1205.19   244.9 1167.35   293.9 1151.91   323.3 1136.17   401.7 1113.72
   489.9 1104.54   578.0 1089.16   656.4 1082.90   764.2 1085.44   950.3 1081.76
  1009.1 1084.80  1038.5 1082.07  1060.4 1076.59  1075.4 1071.73  1087.3 1068.41
  1097.1 1073.75  1126.2 1097.71  1136.0 1101.85  1233.2 1128.07  1301.3 1149.87
  1349.9 1159.71  1427.7 1180.40  1456.9 1191.21  1554.1 1215.85  1641.7 1243.16
#Mann= 3 , 0 , 0
       0     0.1       0  1060.4   0.045       0  1075.4     0.1       0
Bank Sta=  1060.4,  1075.4
Exp/Cntr=0.3,0.1

Type RM Length L Ch R = 1 ,5387,332.702,320.643,309.928
XS GIS Cut Line= 3
     1747413.208      404325.944     1747523.866      403189.921
     1747539.057      402734.922
#Sta/Elev= 30
       0 1229.26    98.4 1220.28   216.5 1191.85   246.0 1179.50   295.2 1168.40
   324.7 1157.61   432.9 1138.02   541.2 1127.37   600.2 1111.36   688.8 1101.41
   777.3 1080.22   826.5 1076.52   905.2 1079.76  1062.7 1078.60  1131.8 1072.17
  1146.8 1065.22  1151.1 1063.47  1170.5 1068.39  1189.8 1084.84  1199.5 1087.94
  1228.6 1109.33  1267.3 1126.78  1277.0 1128.03  1306.1 1145.55  1344.8 1162.16
  1354.5 1162.65  1432.0 1188.36  1509.5 1216.18  1538.5 1230.83  1596.7 1232.64
#Mann= 3 , 0 , 0
       0     0.1       0  1131.8   0.045       0  1146.8     0.1       0
Bank Sta=  1131.8,  1146.8
Exp/Cntr=0.3,0.1

Type RM Length L Ch R = 1 ,5066.4,517.196,525.806,534.416
XS GIS Cut Line= 3
     1748252.918      404031.309     1747787.938      403015.229
     1747570.966      402615.295
#Sta/Elev= 30
       0 1251.63    39.2 1240.41    68.6 1237.27   137.2 1219.13   343.1 1196.62
   372.5 1195.74   441.1 1181.93   509.7 1156.55   519.5 1155.40   597.9 1119.45
   607.7 1118.54   705.7 1071.84   715.5 1069.06   754.7 1071.75   960.6 1071.20
   980.2 1069.66  1002.2 1063.43  1009.6 1062.47  1017.2 1065.53  1039.0 1074.34
  1107.6 1110.25  1127.1 1116.97  1146.5 1128.86  1165.8 1135.37  1194.9 1151.74
  1272.3 1179.70  1349.8 1192.18  1417.5 1199.03  1485.3 1201.57  1572.4 1200.40
#Mann= 3 , 0 , 0
       0     0.1       0  1002.2   0.045       0  1017.2     0.1       0
Bank Sta=  1002.2,  1017.2
Exp/Cntr=0.3,0.1

Type RM Length L Ch R = 1 ,4540.6,376.22,373.931,371.642
XS GIS Cut Line= 3
     1748380.593      403771.048     1748355.759      403099.132
     1748311.845      402258.588
#Sta/Elev= 30
       0 1263.30    29.2 1257.92    58.5 1247.28    87.7 1230.82    97.4 1228.70
   116.9 1218.28   175.4 1203.94   243.6 1177.19   253.4 1176.09   282.6 1162.37
   292.3 1160.83   360.5 1126.99   419.0 1105.14   438.5 1093.03   458.0 1084.79
   477.5 1068.53   497.0 1064.07   691.9 1063.82   720.4 1056.08   731.1 1055.39
   735.4 1056.56   789.8 1079.18   926.8 1126.77   985.6 1153.44  1063.9 1184.17
  1259.6 1233.14  1386.8 1257.11  1416.2 1267.76  1455.3 1275.81  1514.1 1285.35
#Mann= 3 , 0 , 0
       0     0.1       0   720.4   0.045       0   735.4     0.1       0
Bank Sta=   720.4,   735.4
Exp/Cntr=0.3,0.1

Type RM Length L Ch R = 1 ,4166.6,306.347,309.509,312.633
XS GIS Cut Line= 3
     1748797.281      403475.433     1748727.676      403025.788
     1748658.071      402576.144
#Sta/Elev= 30
       0 1155.27    87.1 1129.13   106.5 1121.26   116.2 1120.22   164.6 1100.94
   183.9 1090.52   203.3 1084.90   232.3 1067.31   251.7 1062.08   406.6 1058.95
   445.3 1060.78   455.0 1059.44   474.1 1050.20   484.0 1049.71   489.1 1050.90
   503.4 1057.42   513.1 1058.84   542.1 1074.74   580.9 1090.27   600.2 1095.46
   619.6 1104.76   677.7 1125.48   706.7 1140.40   745.4 1156.18   755.1 1157.65
   784.1 1172.07   803.5 1177.26   822.9 1186.17   832.6 1186.91   910.0 1210.45
#Mann= 3 , 0 , 0
       0     0.1       0   474.1   0.045       0   489.1     0.1       0
Bank Sta=   474.1,   489.1
Exp/Cntr=0.3,0.1

Type RM Length L Ch R = 1 ,3857.1,342.762,341.157,339.567
XS GIS Cut Line= 3
     1749036.941      403426.224     1749031.015      402971.460
     1749024.321      402516.249
#Sta/Elev= 30
       0 1148.30    19.4 1137.86    38.7 1132.20    58.1 1123.10    77.4 1116.71
   106.4 1100.95   116.1 1099.15   135.5 1088.29   154.8 1081.88   183.9 1065.69
   193.5 1064.58   203.2 1060.97   319.3 1057.66   406.4 1058.21   425.8 1054.74
   447.9 1044.75   454.8 1043.17   462.9 1044.73   493.5 1069.33   551.7 1081.94
   629.2 1111.48   648.5 1121.50   706.6 1142.48   726.0 1152.85   745.4 1158.55
   764.8 1168.26   861.6 1195.73   881.0 1203.81   890.7 1205.30   910.1 1214.62
#Mann= 3 , 0 , 0
       0     0.1       0   447.9   0.045       0   462.9     0.1       0
Bank Sta=   447.9,   462.9
Exp/Cntr=0.3,0.1

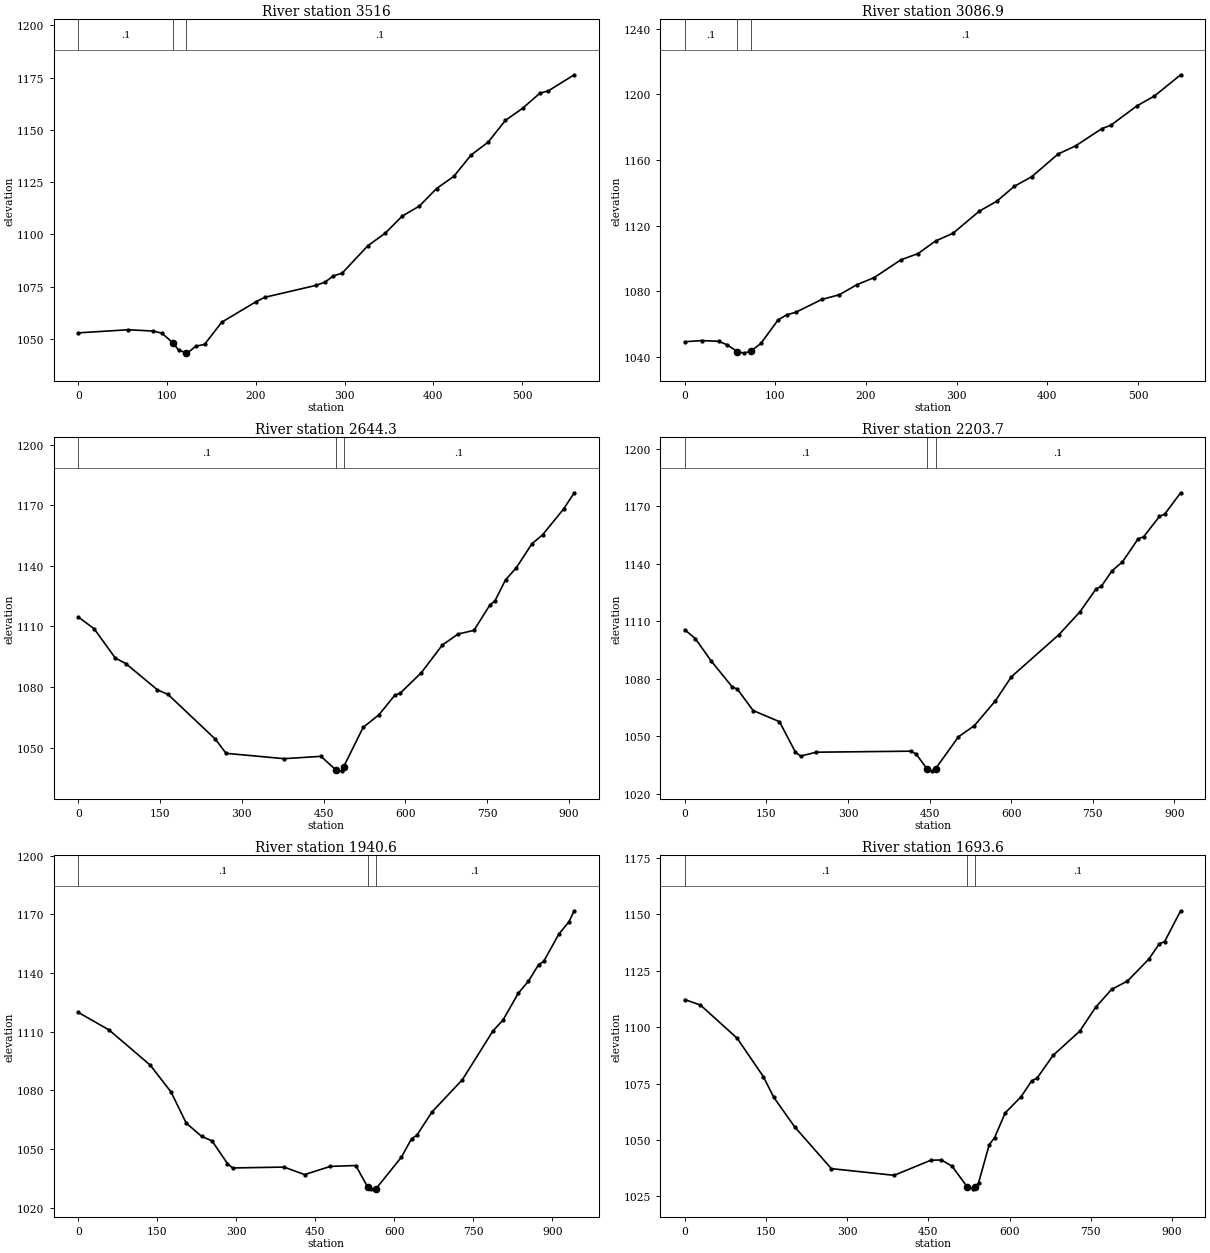
Type RM Length L Ch R = 1 ,3516,418.724,429.104,439.506
XS GIS Cut Line= 3
     1749374.795      403137.827     1749365.974      403034.760
     1749326.398      402581.224
#Sta/Elev= 30
       0 1052.84    56.4 1054.33    84.6 1053.69    94.0 1052.69   106.4 1048.16
   113.1 1044.52   121.4 1043.34   122.8 1043.14   132.5 1046.50   142.2 1047.30
   161.6 1057.94   200.3 1067.76   210.0 1069.84   268.1 1075.59   277.8 1077.08
   287.5 1080.11   297.2 1081.37   326.2 1094.52   345.6 1100.45   365.0 1108.72
   384.3 1113.51   403.7 1121.91   423.1 1127.71   442.5 1137.92   461.8 1144.09
   481.2 1154.48   500.6 1160.29   520.0 1167.48   529.6 1168.63   558.7 1176.30
#Mann= 3 , 0 , 0
       0     0.1       0   106.4   0.045       0   121.4     0.1       0
Bank Sta=   106.4,   121.4
Exp/Cntr=0.3,0.1

Type RM Length L Ch R = 1 ,3086.9,442.01,442.565,443.12
XS GIS Cut Line= 3
     1749764.869      403145.702     1749798.698      403058.812
     1749993.443      402648.822
#Sta/Elev= 30
       0 1049.14    18.6 1049.84    37.3 1049.39    46.6 1047.29      58 1043.07
    65.3 1042.18      73 1043.37    83.9 1048.07   102.9 1062.40   112.6 1065.62
   122.2 1067.04   151.2 1074.95   170.5 1077.80   189.8 1083.91   209.1 1088.31
   238.1 1099.02   257.4 1102.94   276.7 1110.61   296.0 1115.33   325.0 1128.83
   344.3 1134.88   363.6 1143.97   383.0 1149.90   411.9 1163.69   431.2 1168.63
   460.2 1179.19   469.9 1181.16   498.8 1193.01   518.2 1199.08   547.1 1212.00
#Mann= 3 , 0 , 0
       0     0.1       0      58   0.045       0      73     0.1       0
Bank Sta=      58,      73
Exp/Cntr=0.3,0.1

Type RM Length L Ch R = 1 ,2644.3,449.006,440.636,431.51
XS GIS Cut Line= 3
     1750011.486      403690.037     1750187.000      403270.251
     1750362.513      402850.465
#Sta/Elev= 30
       0 1114.71    29.0 1108.86    67.8 1094.38    87.1 1091.64   145.2 1078.61
   164.6 1076.34   251.7 1054.13   271.1 1047.17   377.6 1044.52   445.3 1045.68
     472 1039.10   474.4 1038.35   484.0 1038.63     487 1040.54   522.8 1060.05
   551.8 1066.28   580.9 1075.99   590.5 1076.90   629.3 1087.03   668.0 1100.79
   697.0 1106.26   726.1 1108.09   755.1 1120.53   764.8 1122.79   784.1 1133.10
   803.5 1138.97   832.6 1150.99   851.9 1155.36   890.6 1168.18   910.0 1176.20
#Mann= 3 , 0 , 0
       0     0.1       0     472   0.045       0     487     0.1       0
Bank Sta=     472,     487
Exp/Cntr=0.3,0.1

Type RM Length L Ch R = 1 ,2203.7,263.594,263.014,265.628
XS GIS Cut Line= 3
     1750602.916      403829.939     1750614.150      403375.539
     1750609.513      402918.370
#Sta/Elev= 30
       0 1105.45    19.3 1100.90    48.4 1089.21    87.0 1075.73    96.7 1074.47
   125.7 1063.31   174.1 1057.51   203.1 1041.79   212.8 1039.56   241.8 1041.59
   415.9 1042.12   425.5 1040.58   446.1 1032.63   454.5 1031.71   461.1 1033.00
   503.2 1049.61   532.4 1055.41   571.3 1068.47   600.5 1080.94   688.0 1102.92
   726.9 1114.93   756.1 1126.74   765.8 1128.07   785.3 1136.12   804.7 1140.88
   833.9 1153.00   843.6 1153.93   872.8 1164.59   882.5 1165.82   911.7 1176.90
#Mann= 3 , 0 , 0
       0     0.1       0   446.1   0.045       0   461.1     0.1       0
Bank Sta=   446.1,   461.1
Exp/Cntr=0.3,0.1

Type RM Length L Ch R = 1 ,1940.6,247.693,247.039,243.946
XS GIS Cut Line= 3
     1750829.857      403905.017     1750875.582      403418.838
     1750859.930      402965.766
#Sta/Elev= 30
       0 1119.85    58.6 1110.84   136.7 1092.86   175.8 1079.27   205.1 1063.20
   234.4 1056.44   253.9 1054.17   283.2 1042.61   293.0 1040.33   390.7 1040.78
   429.7 1036.94   478.6 1041.13   526.9 1041.58   549.8 1030.46   555.8 1029.51
   564.8 1029.53   613.7 1045.90   633.0 1055.35   642.7 1056.93   671.6 1068.93
   729.5 1085.49   787.3 1110.33   806.6 1115.97   835.6 1129.68   854.9 1135.82
   874.1 1144.27   883.8 1145.91   912.7 1159.93   932.0 1166.26   941.7 1171.79
#Mann= 3 , 0 , 0
       0     0.1       0   549.8   0.045       0   564.8     0.1       0
Bank Sta=   549.8,   564.8
Exp/Cntr=0.3,0.1

Type RM Length L Ch R = 1 ,1693.6,579.994,577.298,574.571
XS GIS Cut Line= 3
     1751161.734      403829.139     1751102.539      403378.523
     1751111.062      402916.889
#Sta/Elev= 30
       0 1112.22    29.0 1109.78    96.7 1095.10   145.0 1078.13   164.4 1068.92
   203.1 1055.79   270.8 1037.31   386.8 1034.35   454.5 1041.02   474.1 1041.16
   493.8 1038.40   521.6 1029.33   533.1 1028.23   536.6 1029.24   542.9 1031.07
   562.5 1047.88   572.4 1051.02   592.0 1061.98   621.5 1069.21   641.1 1076.25
   651.0 1077.44   680.4 1087.46   729.6 1098.17   759.0 1108.76   788.5 1116.70
   818.0 1120.44   857.3 1130.10   876.9 1136.95   886.7 1137.94   916.2 1151.54
#Mann= 3 , 0 , 0
       0     0.1       0   521.6   0.045       0   536.6     0.1       0
Bank Sta=   521.6,   536.6
Exp/Cntr=0.3,0.1

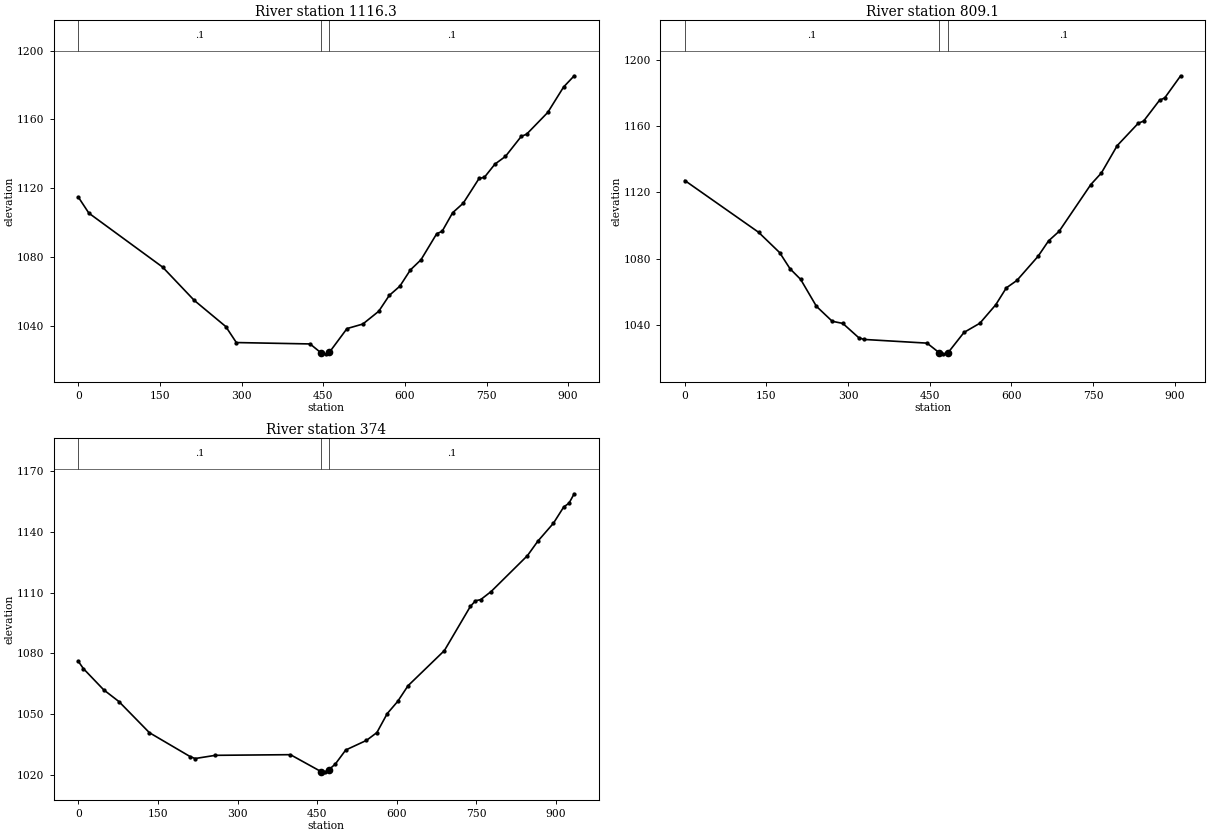
Type RM Length L Ch R = 1 ,1116.3,307.026,307.24,307.446
XS GIS Cut Line= 3
     1751686.138      403796.241     1751629.133      403345.038
     1751572.148      402892.416
#Sta/Elev= 30
       0 1114.76    19.4 1105.42   154.8 1074.03   212.9 1054.66   270.9 1039.40
   290.3 1030.08   425.8 1029.27   446.1 1024.03   454.8 1023.34   461.1 1024.32
   493.6 1038.21   522.7 1040.86   551.9 1048.28   571.3 1057.53   590.7 1062.88
   610.1 1072.37   629.5 1078.25   658.6 1093.53   668.3 1094.79   687.7 1105.66
   707.2 1111.23   736.3 1125.63   746.0 1126.27   765.4 1133.97   784.8 1138.48
   813.9 1150.16   823.6 1151.39   862.5 1164.08   891.6 1178.89   911.0 1185.39
#Mann= 3 , 0 , 0
       0     0.1       0   446.1   0.045       0   461.1     0.1       0
Bank Sta=   446.1,   461.1
Exp/Cntr=0.3,0.1

Type RM Length L Ch R = 1 ,809.1,433.249,435.033,433.751
XS GIS Cut Line= 3
     1751989.595      403772.888     1751932.591      403321.686
     1751875.605      402869.063
#Sta/Elev= 30
       0 1127.21   135.5 1095.96   174.2 1083.69   193.5 1073.85   212.9 1067.47
   241.9 1051.19   270.9 1042.18   290.3 1040.89   319.3 1032.35   329.0 1031.22
   445.1 1028.98   467.8 1023.10   474.2 1022.34   482.8 1022.83   513.0 1035.46
   542.1 1040.99   571.3 1052.14   590.7 1062.35   610.1 1066.82   648.9 1081.36
   668.3 1090.73   687.7 1096.50   746.0 1124.77   765.4 1131.76   794.5 1148.29
   833.3 1161.84   843.0 1163.11   872.2 1175.67   881.9 1177.15   911.0 1190.44
#Mann= 3 , 0 , 0
       0     0.1       0   467.8   0.045       0   482.8     0.1       0
Bank Sta=   467.8,   482.8
Exp/Cntr=0.3,0.1

Type RM Length L Ch R = 1 ,374,371.262,374.038,379.879
XS GIS Cut Line= 4
     1752231.279      403587.356     1752334.463      403309.296
     1752322.160      403131.865     1752193.641      402690.433
#Sta/Elev= 30
       0 1076.06     9.6 1072.45    47.8 1062.01    76.5 1056.22   133.9 1040.87
   210.5 1029.10   220.0 1028.12   258.3 1029.70   399.6 1030.02   457.2 1021.69
   465.1 1021.41   472.2 1022.65   484.2 1025.40   503.8 1032.32   542.9 1037.07
   562.5 1040.92   582.0 1050.28   601.6 1056.26   621.2 1064.03   689.7 1081.37
   738.6 1103.14   748.3 1105.94   758.1 1106.51   777.7 1110.49   846.2 1128.22
   865.7 1135.32   895.1 1144.18   914.6 1152.24   924.4 1154.05   934.2 1158.70
#Mann= 3 , 0 , 0
       0     0.1       0   457.2   0.045       0   472.2     0.1       0
Bank Sta=   457.2,   472.2
Exp/Cntr=0.3,0.1